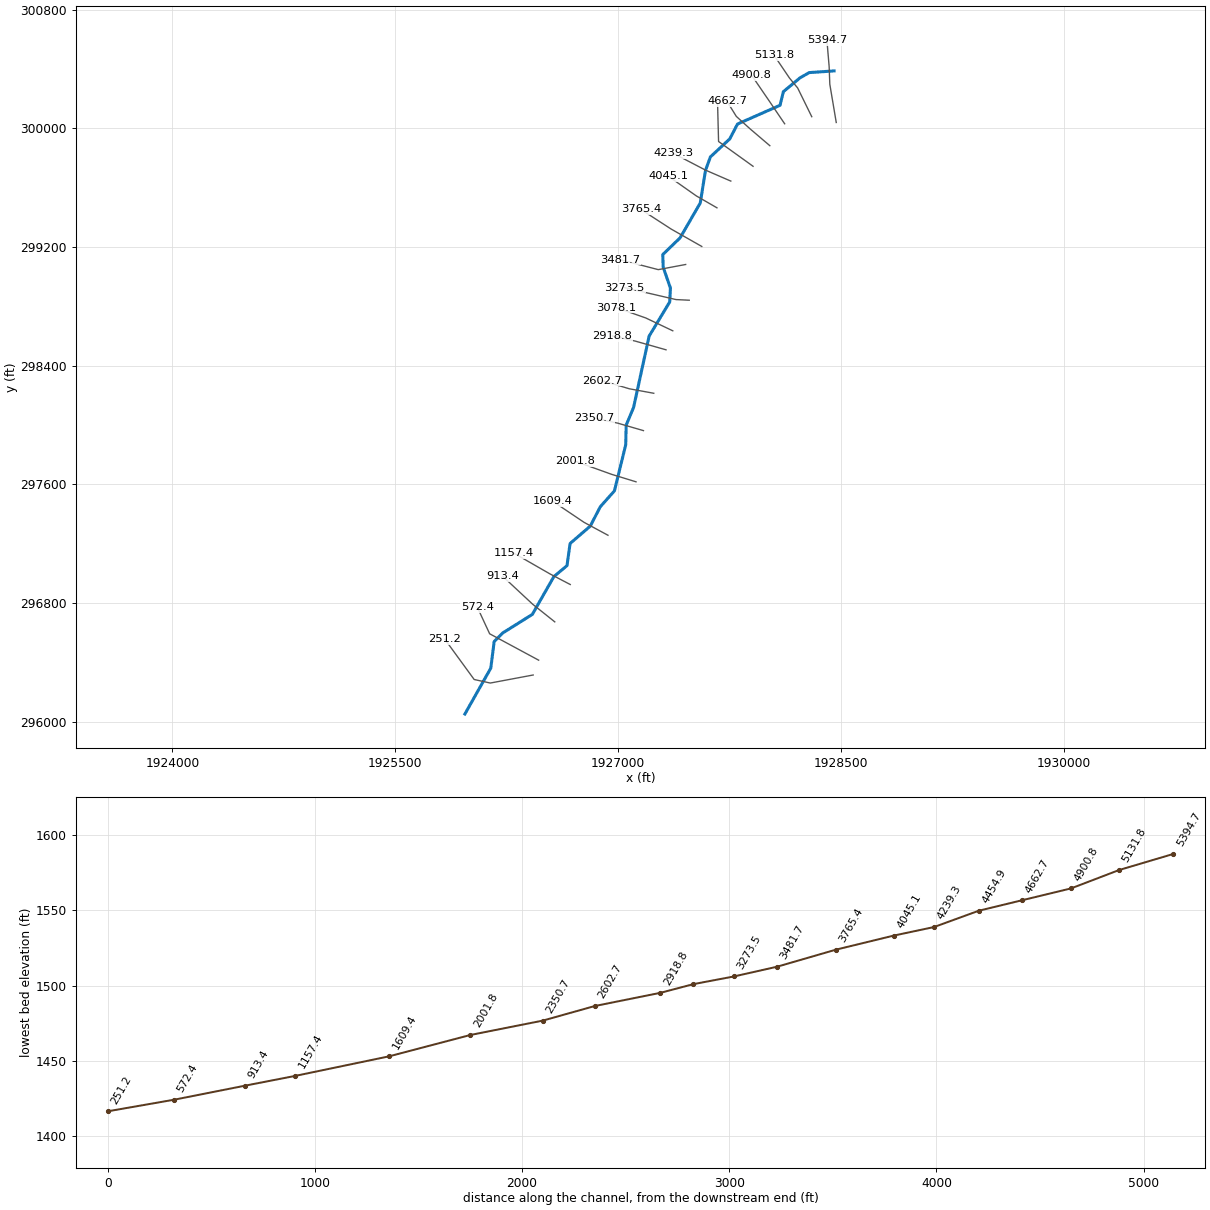
--- MADISONRN.prj (project) ---

Proj Title=MADISONRN
Current Plan=p01
Default Exp/Contr=0,0
English Units
Geom File=g01
Flow File=f01
Plan File=p01
BEGIN DESCRIPTION:
END DESCRIPTION:
DSS Export Rating Curves= 0
DSS Export Rating Curve Sorted= 0
DSS Export Volume Flow Curves= 0
DXF OffsetX= 0
DXF OffsetY= 0
DXF ScaleX= 0
DXF ScaleY= 0

--- MADISONRN.p01 (plan) ---

Plan Title=Floodplain
Program Version=4.00
Geom File=g01
Flow File=f01
K Sum by GR=0
Std Step Tol=0.01
Critical Tol=0.01
Num of Std Step Trials=20
Max Error Tol=0.3
Flow Tol Ratio=0.001
Split Flow NTrial=30
Split Flow Tol=0.02
Split Flow Ratio=0.02
Log Output Level=0
Friction Slope Method=1
Unsteady Friction Slope Method=2
Unsteady Bridges Friction Slope Method=1
Global Log Level=0
CheckData=False
Run HTab=0
Run UNet=0
Run PostProcess=0
UNET Theta=0
UNET Theta Warmup=0
UNET ZTol=0
UNET ZSATol=0
UNET MxIter=0
UNET MaxInSteps=0
UNET DtIC=0
UNET DtMin=0
UNET MaxCRTS=0
UNET WFStab=0
UNET SFStab=0
UNET WFX=0
UNET SFX=0
UNET DSS MLevel=0
UNET DZMax Abort=0
UNET Convert EG Bridges=0
UNET Use Existing IB Tables=0
UNET Froude Limit=0
UNET Froude Power=0
Write IC File=0
Echo Input=False
Echo Output=False
Write Detailed=0

--- MADISONRN.f01 (steady flow) ---

Flow Title=NFF Regression Equation
Program Version=4.00
Number of Profiles=1
Profile Names=P100yr
River Rch & RM=MADISONRN,Main      ,5394.7
590.5143
River Rch & RM=MADISONRN,Main      ,4454.9
595.4867
River Rch & RM=MADISONRN,Main      ,4239.3
861.4670
River Rch & RM=MADISONRN,Main      ,251.2
917.0093
Boundary for River Rch & Prof#=MADISONRN,Main      ,1
Up Type=0
Dn Type=3
Dn Slope=0.026068

--- MADISONRN.g01 (geometry) ---

Geom Title=USGS 10m DEM
Program Version=4.10

River Reach=MADISONRN       ,Main
Reach XY= 30
     1928453.581      300386.657     1928286.244      300375.287
     1928224.612      300339.697     1928112.633      300246.815
     1928090.363      300154.981     1927803.885      300028.587
      1927751.96      299928.535     1927621.513      299806.954
     1927588.584      299716.274     1927553.123      299495.907
      1927417.61      299261.609     1927301.094      299148.892
     1927303.627      299064.039     1927352.446      298922.891
     1927347.659      298829.642       1927209.1      298599.037
     1927104.434       298118.08      1927054.69      297999.564
     1927051.435        297866.1      1926975.48      297555.771
     1926880.472         297449.      1926812.72       297318.14
     1926677.155      297201.495     1926656.208      297052.101
     1926568.088      296978.303      1926422.92      296723.305
     1926222.399      296597.437     1926165.975      296540.146
     1926143.406      296361.326     1925969.013      296051.864

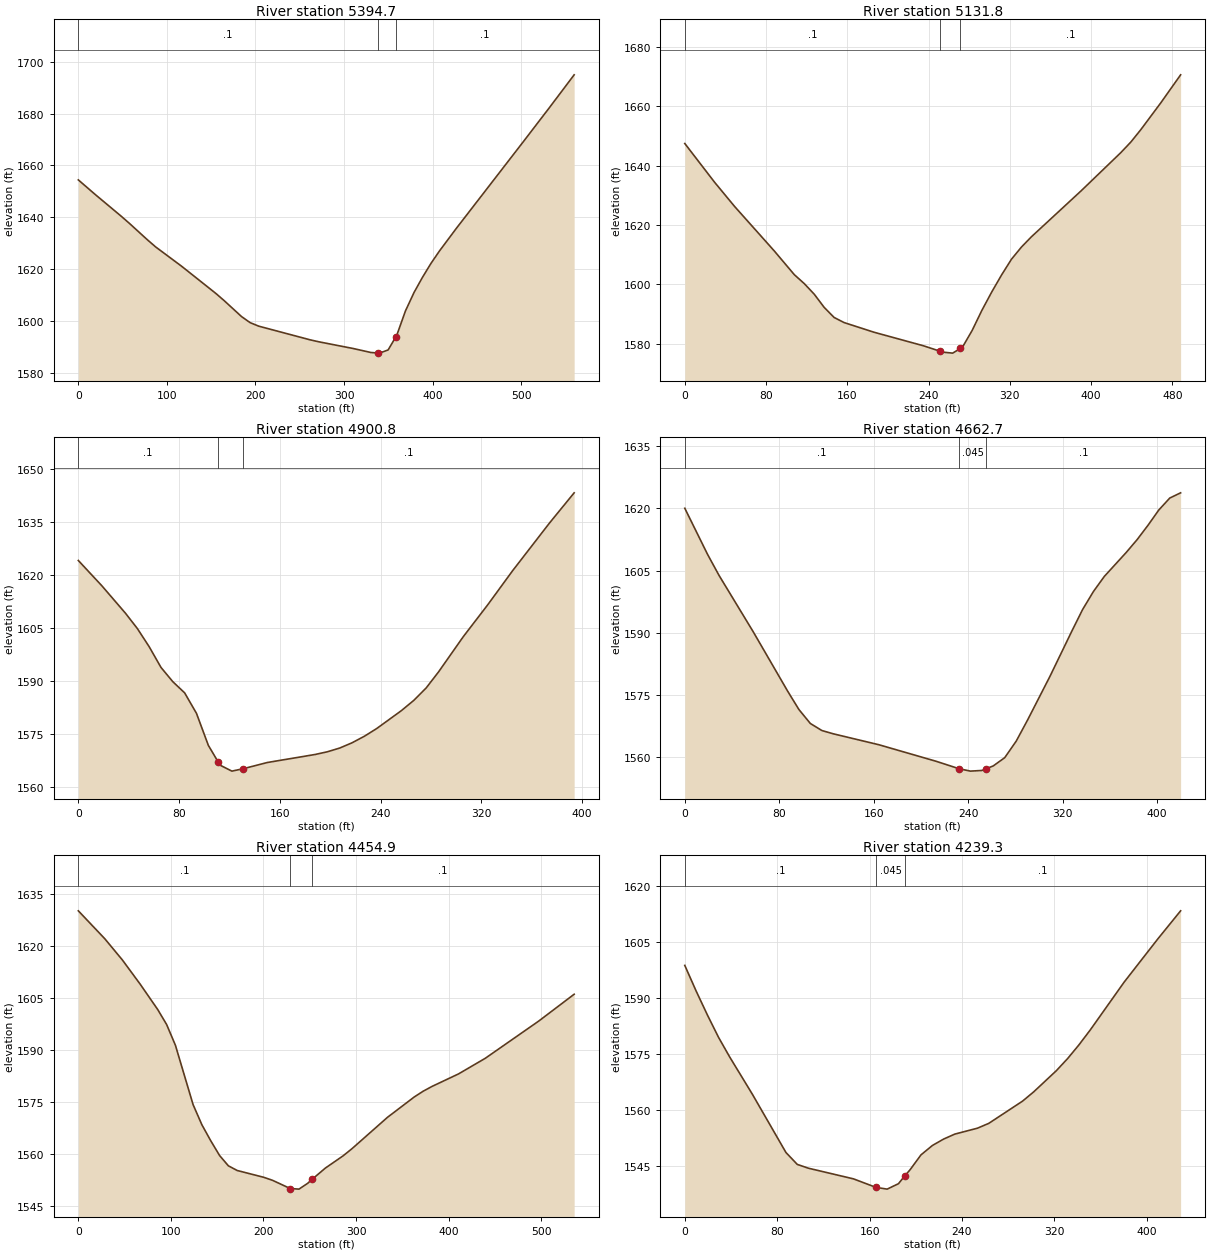
Type RM Length L Ch R = 1 ,5394.7  ,246.4,262.9,279.3
XS GIS Cut Line= 4
     1928468.579      300038.952     1928425.177      300297.199
     1928420.836      300414.386     1928405.645      300594.508
#Sta/Elev= 30
       0  1654.4    19.4 1648.67    48.5 1640.36    58.2 1637.46    77.6  1631.4
    87.3 1628.53   116.4 1621.13   155.2  1610.6   164.9 1607.73   184.3 1601.64
     194  1599.3   203.7 1597.94   261.9 1592.65   271.6  1591.9   310.7 1589.29
   330.3 1587.78   338.5 1587.57     340 1587.53   349.8 1588.75   358.5 1593.78
   359.6 1594.42   369.4 1603.82   379.1 1610.94   388.6 1616.78   398.2 1622.16
   407.7 1626.91   426.7 1635.62   502.8 1669.28   531.4 1682.04   559.9 1694.96
#Mann= 3 , 0 , 0
       0      .1       0   338.5    .045       0   358.5      .1       0
Bank Sta=338.5,358.5
XS Rating Curve= 0 ,0
Exp/Cntr=0.3,0.1

Type RM Length L Ch R = 1 ,5131.8  ,233.3,230.9,228.2
XS GIS Cut Line= 4
     1928303.649      300078.015     1928208.828      300271.705
     1928153.909      300338.431     1928049.742      300492.511
#Sta/Elev= 30
       0 1647.44    29.4 1634.35      49 1626.23    88.2 1611.18   107.8 1603.23
   117.6 1600.22   127.4 1596.65   137.2 1592.21     147  1588.8   156.8 1587.08
   186.2 1583.83   234.9 1579.26   251.4 1577.41   254.1 1577.11   263.7 1576.78
   271.4 1578.37   273.3 1578.76   282.9 1584.44   292.5 1591.23   302.1 1597.35
   311.9 1603.16   321.6 1608.44   331.4 1612.53   341.2 1615.99   390.2  1631.5
   429.3 1644.39   439.1 1647.93   448.9  1652.1   468.5 1661.11   488.1 1670.59
#Mann= 3 , 0 , 0
       0      .1       0   251.4    .045       0   271.4      .1       0
Bank Sta=251.4,271.4
XS Rating Curve= 0 ,0
Exp/Cntr=0.3,0.1

Type RM Length L Ch R = 1 ,4900.8  ,231.5,238.1,244.8
XS GIS Cut Line= 3
     1928121.357      300030.271     1928021.531      300177.841
     1927900.003      300355.792
#Sta/Elev= 30
       0 1624.07    18.8 1616.88    37.5 1609.15    46.9 1604.84    56.3  1599.7
    65.6 1593.89      75 1589.86    84.4  1586.7    93.8 1580.91   103.2 1571.89
     111  1567.2   112.5  1566.3   121.9 1564.61     131  1565.3     150 1567.04
     188 1569.31   197.8 1570.08   207.6 1571.14   217.3 1572.61   227.1 1574.46
   236.9 1576.64   256.5  1581.7   266.3 1584.58   276.1 1588.08   285.9 1592.59
   305.5 1602.52   325.1 1611.61   344.7 1621.16   374.1 1634.68   393.6 1643.17
#Mann= 3 , 0 , 0
       0      .1       0     111    .045       0     131      .1       0
Bank Sta=111,131
XS Rating Curve= 0 ,0
Exp/Cntr=0.3,0.1

Type RM Length L Ch R = 1 ,4662.7  ,205,207.8,210.8
XS GIS Cut Line= 4
     1928021.531      299882.702     1927889.152      299995.549
     1927795.836      300080.185     1927732.902      300182.181
#Sta/Elev= 30
       0    1620    19.3 1608.88      29 1603.82      58 1590.21      87 1575.98
    96.6 1571.52   106.3 1568.15     116 1566.46   125.6 1565.67   164.3 1563.03
   212.7 1559.05   232.1 1557.26   241.8 1556.67   251.5 1556.83   255.4 1557.27
   261.2 1557.93   270.9 1559.92   280.6  1563.9   290.2 1568.97   309.2 1579.52
   327.6 1590.34   336.8  1595.6     346 1599.95   355.2 1603.58   373.7 1609.34
   382.9 1612.42   392.1 1615.87   401.3 1619.57   410.6 1622.46   419.8 1623.72
#Mann= 3 , 0 , 0
       0      .1       0   232.1    .045       0   255.4      .1       0
Bank Sta=232.1,255.4
XS Rating Curve= 0 ,0
Exp/Cntr=0.3,0.1

Type RM Length L Ch R = 1 ,4454.9  ,210.3,215.6,218.8
XS GIS Cut Line= 3
     1927908.683      299743.813     1927676.479      299910.914
     1927669.968       300160.48
#Sta/Elev= 30
       0 1630.18    28.6 1622.11    47.7 1615.94    66.8 1608.99    85.8 1601.64
    95.4 1597.32   104.9 1591.32     124 1574.16   133.5 1568.34     143 1563.75
   152.6 1559.46   162.1 1556.48   171.6 1555.13   200.3 1553.16   209.8 1552.29
   228.9 1549.92   238.4 1549.74   247.9 1551.44   252.5 1552.56     267 1555.84
   286.1 1559.37   295.7 1561.44   334.1 1570.51   362.9 1576.37   372.5 1578.03
   382.1 1579.42   410.9 1583.06   439.7 1587.56   497.3 1598.29   535.7 1606.07
#Mann= 3 , 0 , 0
       0      .1       0   228.9    .045       0   252.5      .1       0
Bank Sta=228.9,252.5
XS Rating Curve= 0 ,0
Exp/Cntr=0.3,0.1

Type RM Length L Ch R = 1 ,4239.3  ,197.4,194.2,192.8
XS GIS Cut Line= 3
     1927758.944      299643.987     1927589.254      299717.676
     1927372.659      299830.619
#Sta/Elev= 30
       0 1598.75     9.7 1591.98    19.5 1585.54    29.2 1579.52      39 1574.19
    58.4 1564.35    87.6  1548.7    97.4 1545.52   107.1  1544.5     146 1541.66
   165.5 1539.38   175.2 1538.91     185 1540.36  190.69 1542.55   194.8 1543.99
   204.5 1548.07   214.3 1550.57   224.1  1552.3   233.8 1553.63   253.4 1555.21
   263.2  1556.5   292.5 1562.46   302.2 1564.96   321.8 1570.62   331.6 1573.88
   341.3 1577.51   351.1  1581.5   380.4 1594.28   409.7 1605.89   429.3 1613.35
#Mann= 3 , 0 , 0
       0      .1       0   165.5    .045       0  190.69      .1       0
Bank Sta=165.5,190.69
XS Rating Curve= 0 ,0
Exp/Cntr=0.3,0.1

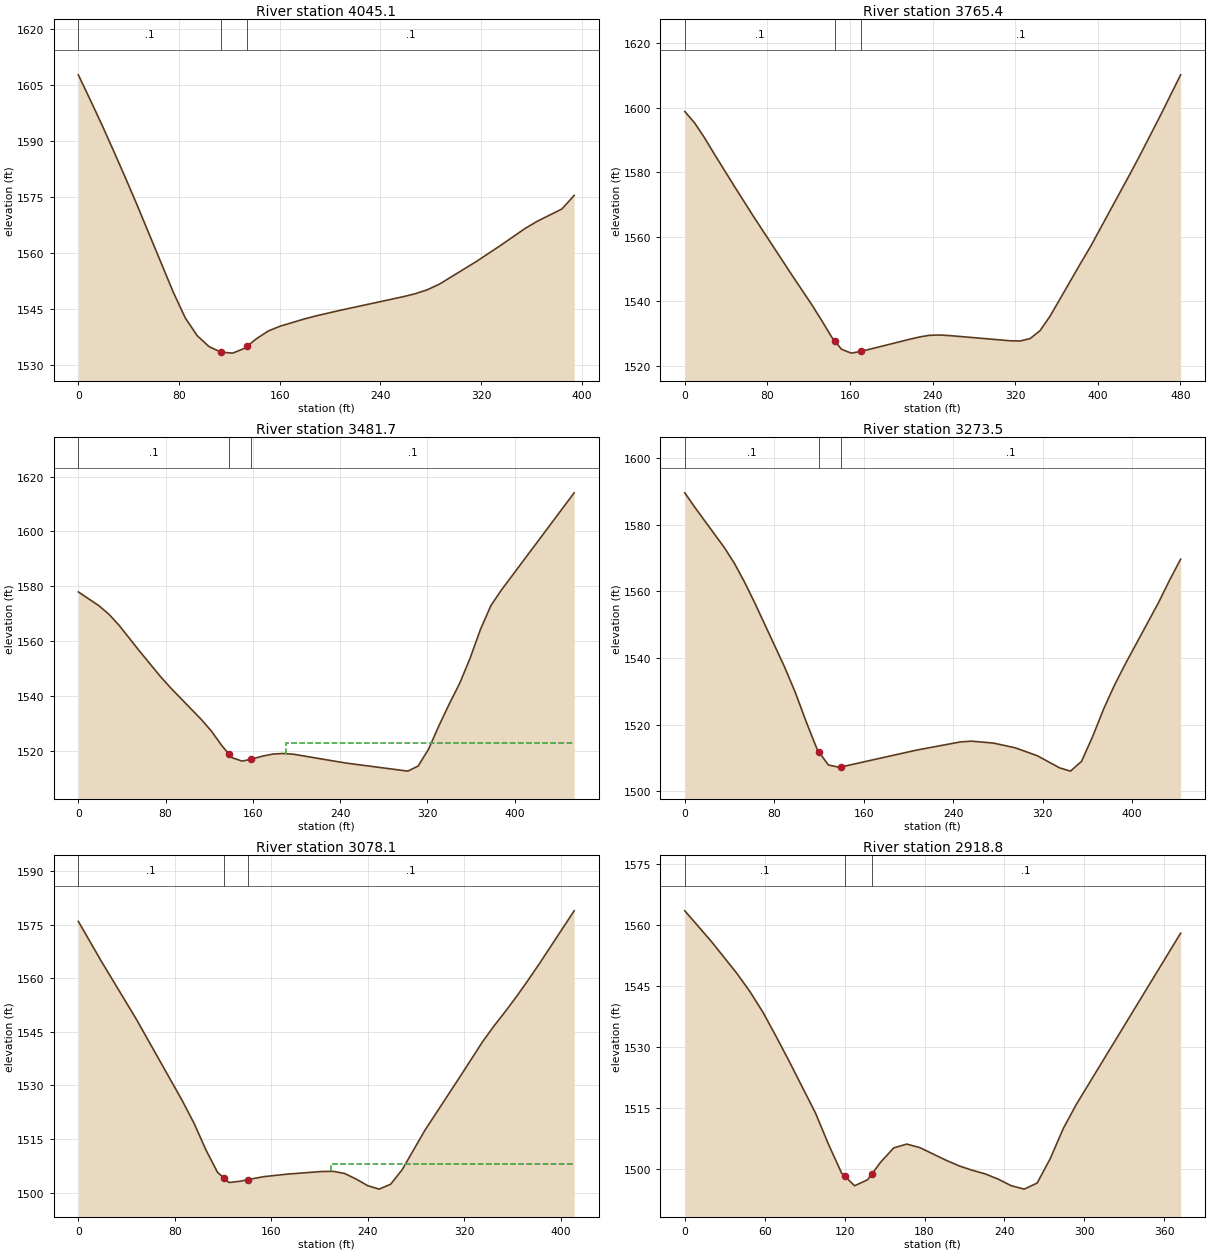
Type RM Length L Ch R = 1 ,4045.1  ,279.1,279.7,280.2
XS GIS Cut Line= 3
     1927665.628      299463.865     1927526.739       299544.16
     1927335.767      299678.709
#Sta/Elev= 30
       0 1607.68     9.4 1601.03    18.9  1594.2    28.3 1587.12    37.8 1579.85
    47.2 1572.45    75.5 1549.49    84.9  1542.7    94.4 1537.93   103.8 1534.99
   113.2  1533.5   122.7 1533.23   132.1 1534.53   134.3 1535.13   141.6  1537.1
     151 1539.16   160.4 1540.44   179.9  1542.4   189.6 1543.25   209.1 1544.76
   257.8  1548.3   267.5  1549.1   277.2 1550.16     287  1551.7   316.2 1557.72
   335.6 1562.06   355.1  1566.6   364.8 1568.52   384.3  1571.8     394 1575.41
#Mann= 3 , 0 , 0
       0      .1       0   113.2    .045       0   134.3      .1       0
Bank Sta=113.2,134.3
XS Rating Curve= 0 ,0
Exp/Cntr=0.3,0.1

Type RM Length L Ch R = 1 ,3765.4  ,266.3,283.7,301.1
XS GIS Cut Line= 3
     1927563.631      299203.449     1927357.468      299320.636
     1927153.475      299453.015
#Sta/Elev= 30
       0 1598.84     9.5  1595.3      19 1590.74    28.5 1585.71    47.4 1575.95
    66.4 1566.35   104.3 1547.82   123.3 1538.75   132.8 1533.87   142.3 1528.83
   145.4 1527.59   151.8 1525.03   161.3 1523.85   170.7 1524.38   218.2 1528.18
   227.7 1528.88   237.1 1529.38   246.9 1529.47   256.6 1529.29     315 1527.69
   324.7 1527.61   334.4 1528.35   344.1 1530.81   353.9 1535.35     383 1551.51
   392.8  1556.8   431.7 1579.71   441.4 1585.56   460.9 1597.72   480.3 1610.22
#Mann= 3 , 0 , 0
       0      .1       0   145.4    .045       0   170.7      .1       0
Bank Sta=145.4,170.7
XS Rating Curve= 0 ,0
Exp/Cntr=0.3,0.1

Type RM Length L Ch R = 1 ,3481.7  ,217.9,208.2,197.9
XS GIS Cut Line= 3
     1927455.124      299081.921     1927270.663      299047.199
     1927012.416      299114.473
#Sta/Elev= 30
       0 1577.91    18.8  1572.9    28.2  1569.7    37.5 1565.67    56.3 1556.22
    75.1 1547.13    84.5 1542.96   112.6 1531.43     122 1527.15   131.4 1521.91
     138 1518.76   140.8 1517.43   150.2 1516.18     158 1516.82   168.9 1517.99
   178.3 1518.73   187.7 1518.96   197.2 1518.69   244.9 1515.49   302.1 1512.52
   311.6 1514.39   321.1 1520.54   330.7 1529.14   340.2 1537.12   349.7 1544.61
   359.3 1553.83   368.8 1564.33   378.3 1572.95   387.8 1578.54   454.6 1614.06
#Mann= 3 , 0 , 0
       0      .1       0     138    .045       0     158      .1       0
#XS Ineff= 2 , 0
                          190.23         1522.62
Permanent Ineff=
       F       F
Bank Sta=138,158
XS Rating Curve= 0 ,0
Exp/Cntr=0.3,0.1

Type RM Length L Ch R = 1 ,3273.5  ,200.9,195.4,190.1
XS GIS Cut Line= 3
     1927478.996      298841.035      1927390.02      298845.376
     1927044.968      298925.671
#Sta/Elev= 30
       0 1589.63     8.9 1585.32    35.6 1573.07    44.5 1568.37    53.4 1562.84
    62.4  1556.7    89.1 1537.42    98.9 1529.62   108.8 1520.68   118.6  1512.4
   120.1 1511.71   128.4  1507.9   138.3  1507.2   140.1 1507.33   207.2 1512.36
   246.5 1514.82   256.4 1515.05   276.1 1514.47   295.7 1513.03   315.4 1510.65
   335.1 1507.04   344.9 1506.05   354.8 1508.99   364.6 1516.35   374.5 1524.67
   384.3  1531.9   394.2 1538.39   423.7 1556.71   433.5 1563.38   443.4  1569.7
#Mann= 3 , 0 , 0
       0      .1       0   120.1    .045       0   140.1      .1       0
#XS Ineff= 2 , 0
                          258.08         1514.88
Permanent Ineff=
       F       F
Bank Sta=120.1,140.1
XS Rating Curve= 0 ,0
Exp/Cntr=0.3,0.1

Type RM Length L Ch R = 1 ,3078.1  ,155.2,159.3,163.5
XS GIS Cut Line= 3
     1927368.319      298634.872     1927186.027      298721.678
     1926988.545      298791.122
#Sta/Elev= 30
       0 1575.95    19.2 1564.72    48.1 1548.56    86.5 1525.55    96.2 1519.24
   105.8 1511.95   115.4 1505.68   120.4 1504.18     125  1502.8   134.6 1503.18
   140.4 1503.61   153.8 1504.44   173.1 1505.15   201.9 1505.89   211.4 1505.93
   220.9 1505.33   230.4 1503.77     240 1501.92   249.5 1500.95     259 1502.32
   268.5 1506.36   287.5 1517.48   316.1 1532.21   335.1 1542.16   344.6  1546.6
   354.2 1550.74   363.7 1555.04   373.2 1559.57   382.7 1564.28   411.2 1578.91
#Mann= 3 , 0 , 0
       0      .1       0   120.4    .045       0   140.4      .1       0
#XS Ineff= 2 , 0
                          209.42         1507.87
Permanent Ineff=
       F       F
Bank Sta=120.4,140.4
XS Rating Curve= 0 ,0
Exp/Cntr=0.3,0.1

Type RM Length L Ch R = 1 ,2918.8  ,313.7,316.2,318.5
XS GIS Cut Line= 3
     1927322.746      298506.834     1927115.207      298565.687
     1926962.503       298600.15
#Sta/Elev= 30
       0 1563.55    19.6 1556.17    39.2 1548.14      49 1543.67    58.8 1538.57
    68.6 1532.67    78.4 1526.57    98.1 1513.89   107.9 1506.19   117.7 1499.14
   120.3  1498.3   127.5 1495.99   137.3 1497.48   140.3 1498.81   147.1 1501.82
   156.9  1505.3   166.7 1506.24   176.5 1505.37   196.1 1502.28   205.9 1500.89
   215.7 1499.82   225.5 1498.92   235.3 1497.63   245.1 1496.01   254.9 1495.17
   264.6 1496.68   274.4 1502.67   284.2 1510.07     294    1516   372.3 1558.06
#Mann= 3 , 0 , 0
       0      .1       0   120.3    .045       0   140.3      .1       0
#XS Ineff= 2 , 0
                          166.14         1505.52
Permanent Ineff=
       F       F
Bank Sta=120.3,140.3
XS Rating Curve= 0 ,0
Exp/Cntr=0.3,0.1

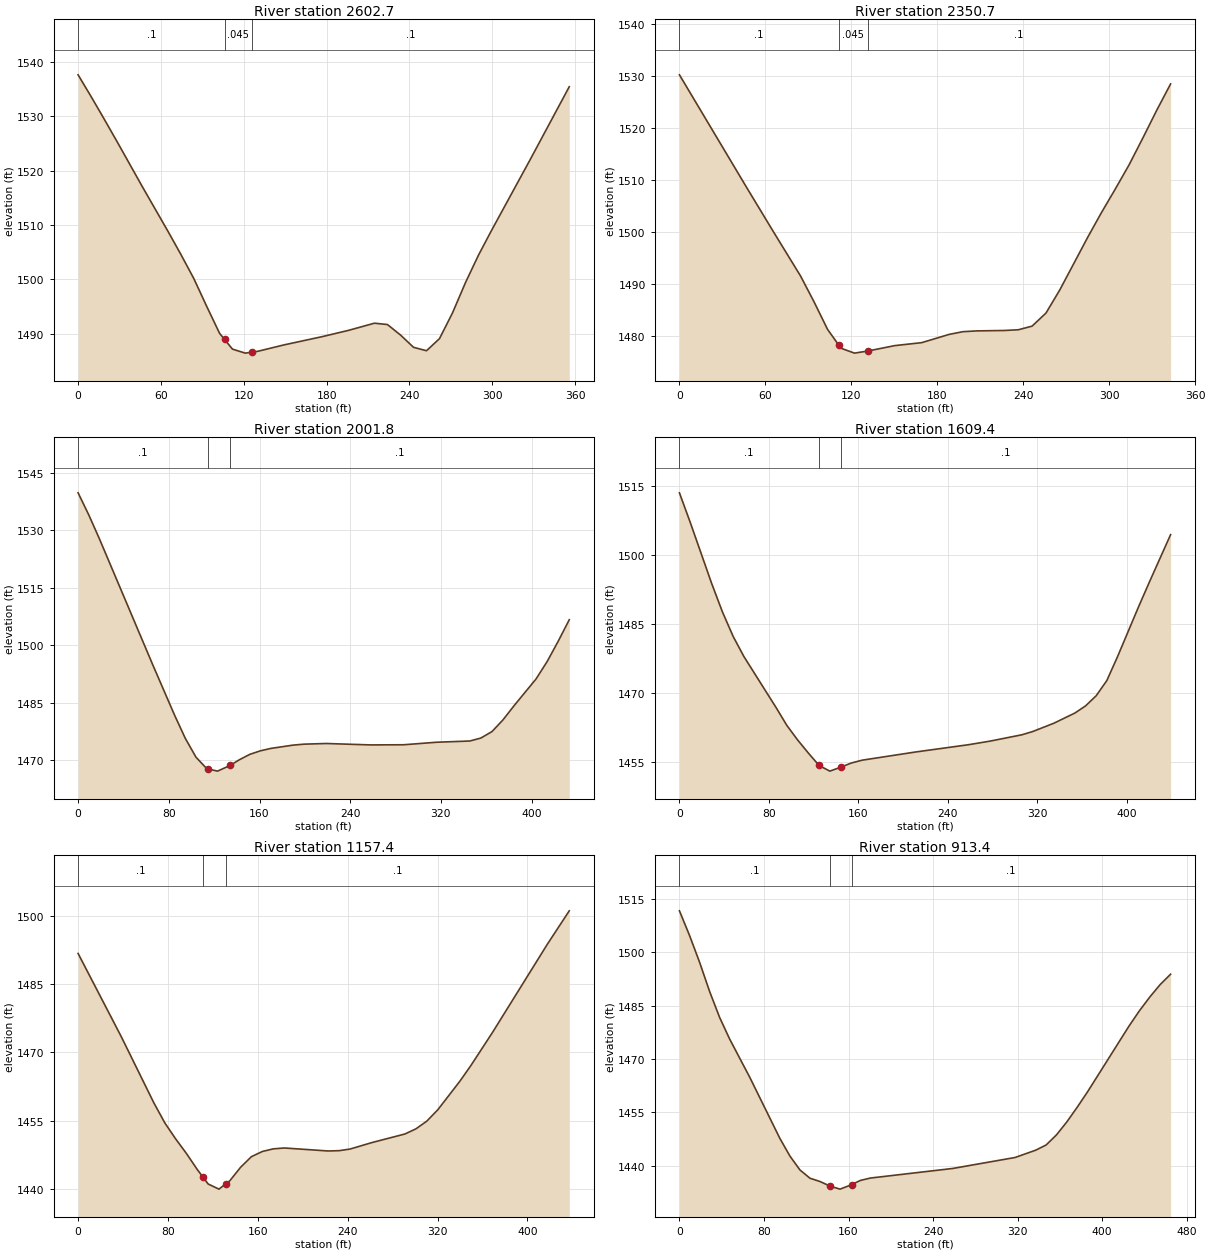
Type RM Length L Ch R = 1 ,2602.7  ,254.3,251.9,249.2
XS GIS Cut Line= 3
     1927240.281      298213.865      1927075.35      298244.247
     1926895.229      298298.501
#Sta/Elev= 30
       0 1537.63     9.3 1533.68    18.6 1529.62      28 1525.44    46.6 1517.02
    65.2 1508.79    74.5 1504.56    83.8 1500.15    93.2    1495   102.5 1490.05
   106.1 1488.93   111.8 1487.15   121.1 1486.41   126.1  1486.6   130.4 1486.76
   149.1 1487.92   177.1 1489.46   195.9  1490.6   214.7 1491.92   224.1 1491.67
   233.6 1489.73     243 1487.48   252.4 1486.85   261.8 1489.08   271.2  1493.8
   280.6 1499.38     290 1504.42   299.4 1508.95   327.6 1522.08   355.8 1535.44
#Mann= 3 , 0 , 0
       0      .1       0   106.1    .045       0   126.1      .1       0
#XS Ineff= 2 , 0
                          215.01         1491.48
Permanent Ineff=
       F       F
Bank Sta=106.1,126.1
XS Rating Curve= 0 ,0
Exp/Cntr=0.3,0.1

Type RM Length L Ch R = 1 ,2350.7  ,349.1,349,348.4
XS GIS Cut Line= 3
     1927170.836      297962.129     1926999.395      298012.042
     1926838.805      298046.765
#Sta/Elev= 27
       0 1530.27      47 1508.54    65.8 1499.97    84.6 1491.51      94 1486.54
   103.4 1481.26   111.4 1478.16   112.8 1477.62   122.2 1476.68   131.4 1477.08
   150.4 1478.13   169.2  1478.7   188.2 1480.28   197.9 1480.81   207.6 1480.96
   226.9 1481.04   236.6 1481.18   246.2 1481.88   255.9  1484.4   265.5 1488.83
   284.9 1498.92   294.5 1503.68   304.2 1508.24   313.9 1512.93   323.5 1518.09
   333.2 1523.44   342.9 1528.52
#Mann= 3 , 0 , 0
       0      .1       0   111.4    .045       0   131.4      .1       0
Bank Sta=111.4,131.4
XS Rating Curve= 0 ,0
Exp/Cntr=0.3,0.1

Type RM Length L Ch R = 1 ,2001.8  ,397,392.4,387.1
XS GIS Cut Line= 3
     1927120.923      297617.077     1926958.163       297666.99
     1926710.767      297755.966
#Sta/Elev= 30
       0 1539.77     9.5 1533.96    18.9  1527.7    66.2 1494.65    85.1 1481.74
    94.6 1475.67     104 1470.77   113.5 1467.78   114.4 1467.72     123 1467.14
   134.4 1468.67   141.9 1470.05   151.3  1471.5   160.8 1472.44   170.2 1473.08
   189.7 1473.93   199.4 1474.18   218.9 1474.35   257.9 1473.98   287.1 1474.02
   316.3 1474.68   345.5    1475   355.2 1475.77     365 1477.45   374.7  1480.5
   384.5 1484.21   403.9 1491.19   413.7 1495.74   423.4 1501.01   433.2 1506.65
#Mann= 3 , 0 , 0
       0      .1       0   114.4    .045       0   134.4      .1       0
Bank Sta=114.4,134.4
XS Rating Curve= 0 ,0
Exp/Cntr=0.3,0.1

Type RM Length L Ch R = 1 ,1609.4  ,451.2,452,452.4
XS GIS Cut Line= 3
     1926932.121      297256.834     1926771.531       297343.64
     1926558.857      297486.869
#Sta/Elev= 30
       0 1513.47     9.6 1507.08    28.8 1493.76    38.4 1487.59      48 1482.24
    57.6 1477.87    86.5 1466.72    96.1 1462.85   105.7  1459.7   115.3 1456.85
   124.4 1454.29   124.9 1454.15   134.5 1452.94   144.4 1453.82   153.7 1454.71
   163.3 1455.32     211  1457.1   258.5 1458.69   277.5 1459.46     306 1460.84
   315.5 1461.53   334.5 1463.34   353.5 1465.58     363 1467.13   372.5 1469.34
     382 1472.64   391.5  1477.8   410.5 1488.76     420 1494.04     439 1504.38
#Mann= 3 , 0 , 0
       0      .1       0   124.4    .045       0   144.4      .1       0
Bank Sta=124.4,144.4
XS Rating Curve= 0 ,0
Exp/Cntr=0.3,0.1

Type RM Length L Ch R = 1 ,1157.4  ,248.6,244,238.8
XS GIS Cut Line= 3
     1926678.215      296924.803     1926541.496      296996.417
      1926296.27      297137.476
#Sta/Elev= 30
       0 1491.68    38.6 1473.34    67.5 1458.86    77.2  1454.5    86.8    1451
    96.5 1447.76   106.1 1444.26   111.4 1442.52   115.8 1441.08   125.4 1439.96
   131.4  1441.1     135 1441.78   144.7 1444.77   154.3 1447.09   164.1 1448.23
   173.8  1448.8   183.6 1448.99   222.6 1448.33   232.4  1448.4   242.1 1448.76
   261.6 1450.18   290.9 1452.06   300.7 1453.19   310.4 1454.88   320.2 1457.38
   339.7  1463.6   349.4    1467     369  1474.4   417.7 1493.71   437.2 1501.04
#Mann= 3 , 0 , 0
       0      .1       0   111.4    .045       0   131.4      .1       0
Bank Sta=111.4,131.4
XS Rating Curve= 0 ,0
Exp/Cntr=0.3,0.1

Type RM Length L Ch R = 1 ,913.4   ,336,341,345.5
XS GIS Cut Line= 3
     1926574.048      296673.067     1926425.564       296791.71
     1926224.656      296979.056
#Sta/Elev= 30
       0 1511.62     9.5 1504.75      19 1497.23    28.5 1489.01      38 1481.68
    47.5  1475.6    66.5 1464.87      95  1447.7   104.5 1442.73     114 1438.81
   123.5 1436.48     133 1435.55   142.9 1434.21     152 1433.41   162.9 1434.65
   171.1 1435.84   180.6 1436.52   258.7 1439.22   317.6  1442.3   337.2 1444.36
     347 1445.82   356.8 1448.65   366.7 1452.34   376.5 1456.46   386.3  1460.8
   425.5 1479.26   435.3 1483.53   445.2 1487.43     455 1490.92   464.8 1493.81
#Mann= 3 , 0 , 0
       0      .1       0   142.9    .045       0   162.9      .1       0
Bank Sta=142.9,162.9
XS Rating Curve= 0 ,0
Exp/Cntr=0.3,0.1

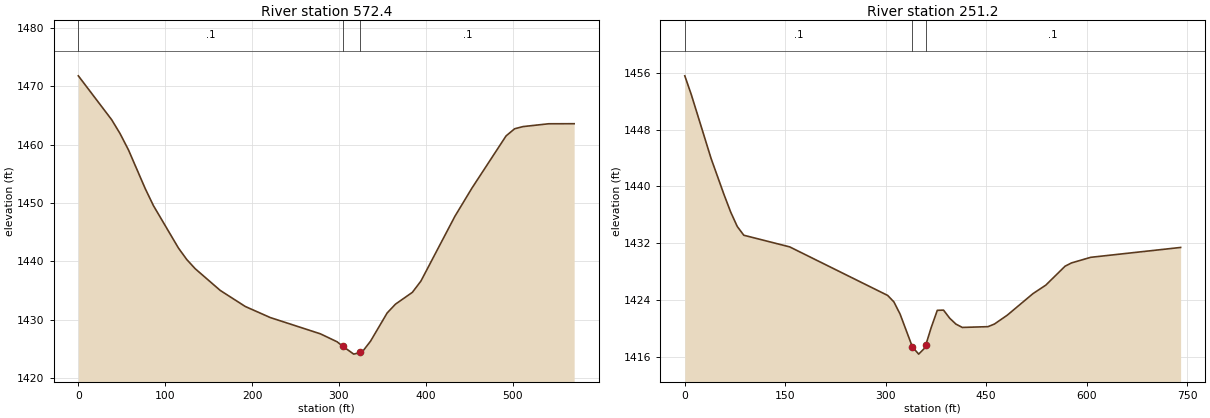
Type RM Length L Ch R = 1 ,572.4   ,314.2,321.2,328.4
XS GIS Cut Line= 3
     1926465.541       296414.82      1926135.68      296592.771
     1926053.215      296770.723
#Sta/Elev= 30
       0 1471.82    38.4 1464.29      48 1461.93    57.7 1459.13    76.9 1452.53
    86.5 1449.56   115.3 1442.29   124.9 1440.32   134.5 1438.76   163.4 1435.03
   192.2 1432.28     221 1430.38   278.7 1427.59   297.9 1426.23   304.8 1425.42
   317.1 1424.11   324.8  1424.4   326.8 1424.47   336.4 1426.32   355.6 1431.17
   365.2 1432.68   384.6  1434.7   394.4 1436.62   433.6 1447.74   453.2 1452.57
   492.5 1461.52   502.3 1462.74   512.1 1463.12   541.5  1463.6   570.9 1463.61
#Mann= 3 , 0 , 0
       0      .1       0   304.8    .045       0   324.8      .1       0
Bank Sta=304.8,324.8
XS Rating Curve= 0 ,0
Exp/Cntr=0.3,0.1

Type RM Length L Ch R = 1 ,251.2   ,259.8,251.2,242.7
XS GIS Cut Line= 4
     1926428.649      296314.994      1926140.02       296260.74
     1926031.513      296284.612     1925834.031      296555.879
#Sta/Elev= 30
       0 1455.59     9.8 1452.92    39.2 1443.96    58.7 1438.82    68.5  1436.4
    78.3 1434.37    88.1 1433.13   156.6 1431.49   302.9 1424.65   312.2 1423.74
   321.5 1422.01   339.8  1417.4   349.2 1416.38   358.5 1417.26   359.8 1417.66
   367.8  1420.1     377 1422.55   386.3 1422.58   395.5 1421.44   404.8 1420.61
   414.4 1420.14   452.7 1420.25   462.3 1420.62   481.5 1421.87   519.8  1424.9
     539  1426.1   567.8 1428.77   577.4 1429.23   606.1 1430.02   740.3 1431.41
#Mann= 3 , 0 , 0
       0      .1       0   339.8    .045       0   359.8      .1       0
#XS Ineff= 2 , 0
                          378.36         1422.43
Permanent Ineff=
       F       F
Bank Sta=339.8,359.8
XS Rating Curve= 0 ,0
Exp/Cntr=0.3,0.1

Chan Stop Cuts=-1
Use User Specified Reach Order=0
Composite Channel Slope=5